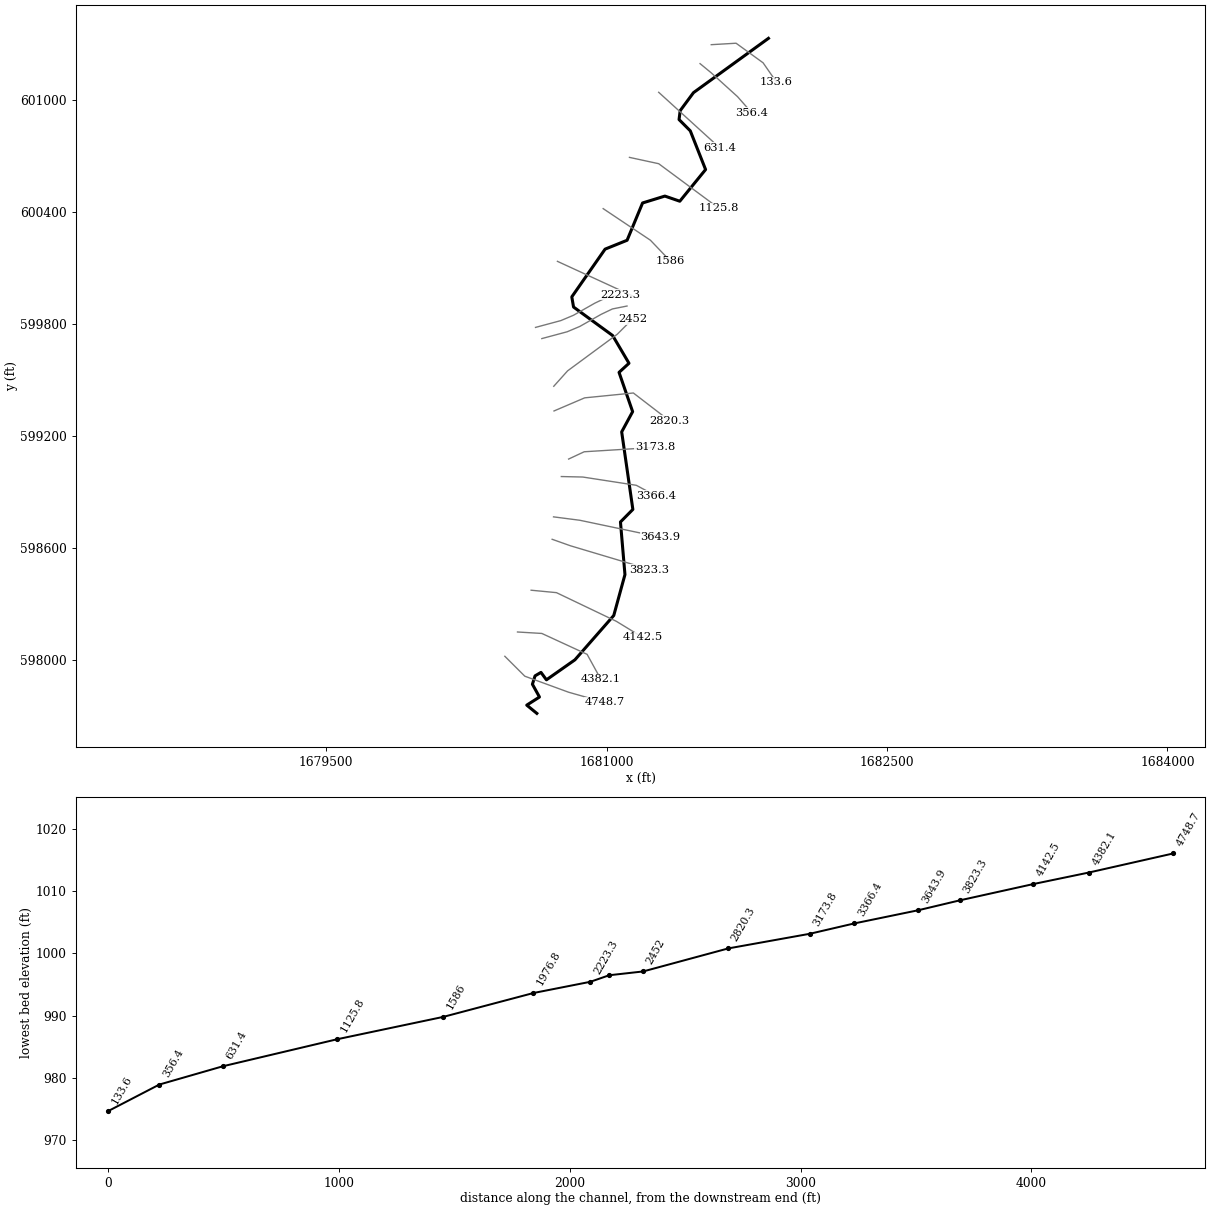
--- RCSRN.prj (project) ---

Proj Title=RCSRN
Current Plan=p01
Default Exp/Contr=0,0
English Units
Geom File=g01
Flow File=f01
Plan File=p01
BEGIN DESCRIPTION:
END DESCRIPTION:
DSS Export Rating Curves= 0
DSS Export Rating Curve Sorted= 0
DSS Export Volume Flow Curves= 0
DXF OffsetX= 0
DXF OffsetY= 0
DXF ScaleX= 0
DXF ScaleY= 0

--- RCSRN.p01 (plan) ---

Plan Title=Floodplain
Program Version=4.00
Geom File=g01
Flow File=f01
K Sum by GR=0
Std Step Tol=0.01
Critical Tol=0.01
Num of Std Step Trials=20
Max Error Tol=0.3
Flow Tol Ratio=0.001
Split Flow NTrial=30
Split Flow Tol=0.02
Split Flow Ratio=0.02
Log Output Level=0
Friction Slope Method=1
Unsteady Friction Slope Method=2
Unsteady Bridges Friction Slope Method=1
Global Log Level=0
CheckData=False
Run HTab=0
Run UNet=0
Run PostProcess=0
UNET Theta=0
UNET Theta Warmup=0
UNET ZTol=0
UNET ZSATol=0
UNET MxIter=0
UNET MaxInSteps=0
UNET DtIC=0
UNET DtMin=0
UNET MaxCRTS=0
UNET WFStab=0
UNET SFStab=0
UNET WFX=0
UNET SFX=0
UNET DSS MLevel=0
UNET DZMax Abort=0
UNET Convert EG Bridges=0
UNET Use Existing IB Tables=0
UNET Froude Limit=0
UNET Froude Power=0
Write IC File=0
Echo Input=False
Echo Output=False
Write Detailed=0

--- RCSRN.f01 (steady flow) ---

Flow Title=NFF Regression Equation
Program Version=4.00
Number of Profiles=1
Profile Names=P100yr
River Rch & RM=RCSRN,Main      ,4748.7
1051.764
River Rch & RM=RCSRN,Main      ,2452
1100.433
River Rch & RM=RCSRN,Main      ,1976.8
1230.078
River Rch & RM=RCSRN,Main      ,133.6
1246.211
Boundary for River Rch & Prof#=RCSRN,Main      ,1
Up Type=0
Dn Type=3
Dn Slope=0.012878

--- RCSRN.g01 (geometry) ---

Geom Title=USGS 10m DEM
Program Version=4.10

River Reach=RCSRN           ,Main
Reach XY= 30
     1680626.614      597713.832     1680572.664      597757.967
      1680640.72      597801.419      1680602.96      597869.996
     1680617.066      597914.918      1680648.75      597933.581
     1680677.915      597893.601      1680830.26      598000.855
     1681038.158      598238.653     1681097.988      598457.729
     1681073.966      598739.955     1681140.272      598807.158
     1681080.476      599222.811      1681139.07      599331.318
      1681066.37      599541.821     1681119.539      599590.649
     1681032.028       599739.46        1680823.      599892.108
     1680813.625      599946.622      1680991.75      600202.525
     1681109.459      600250.094     1681192.238      600450.024
     1681311.596      600486.917     1681391.403      600459.339
     1681529.323      600629.159     1681447.448      600836.711
      1681387.44      600897.095     1681393.281      600944.698
     1681464.591      601041.387     1681865.634      601332.567

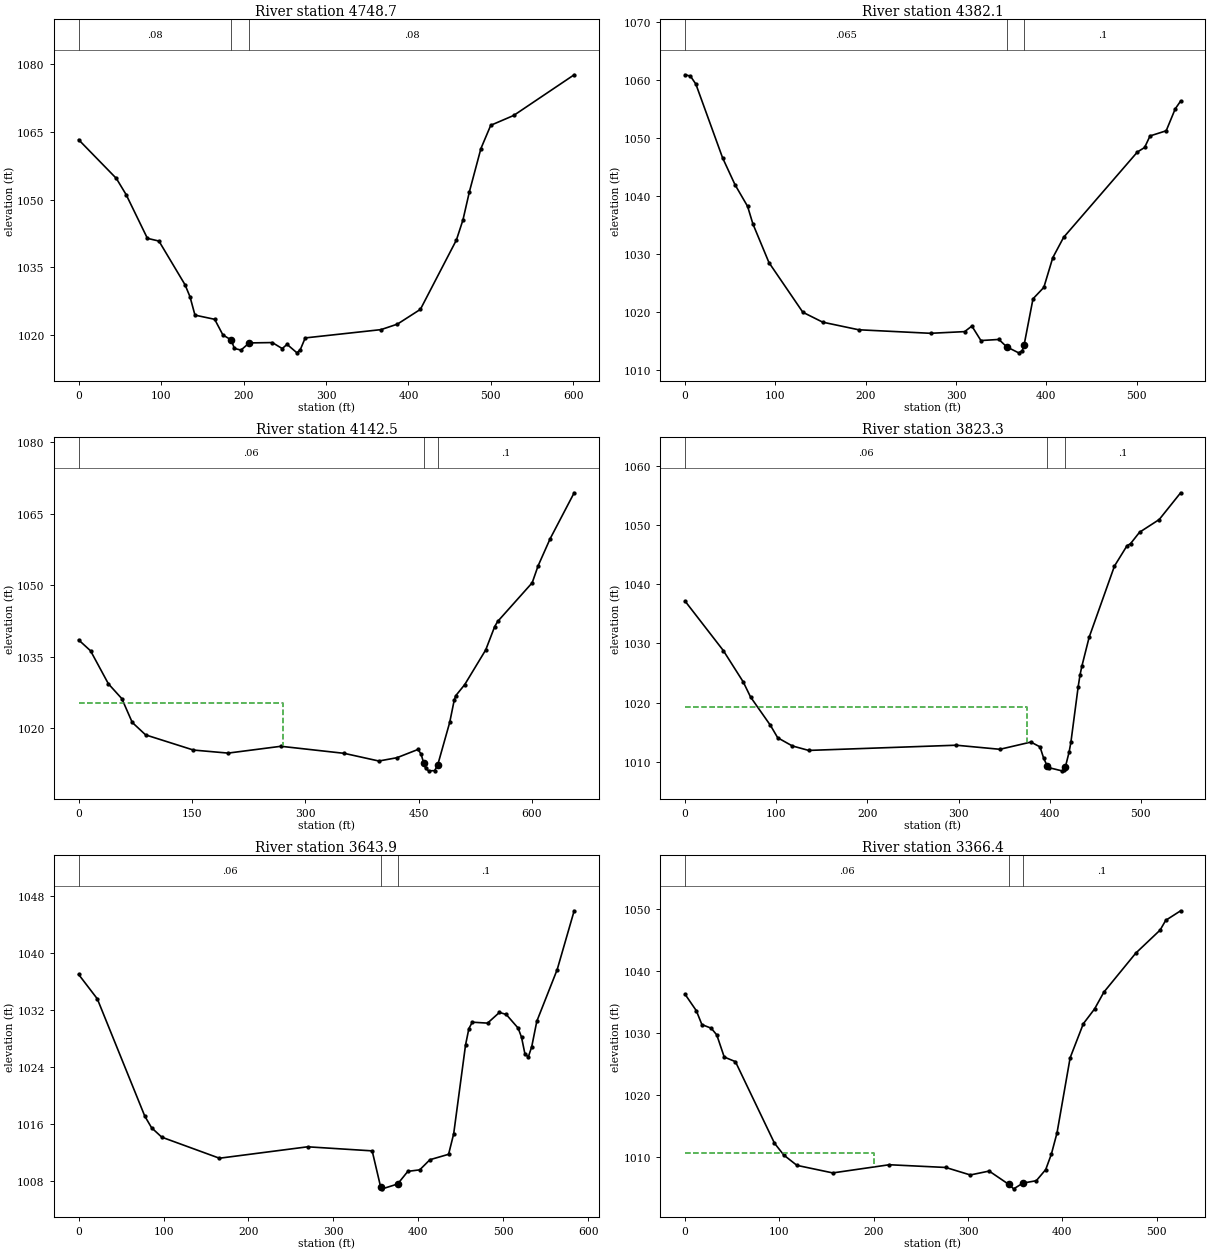
Type RM Length L Ch R = 1 ,4748.7  ,360.7,366.6,342.8
XS GIS Cut Line= 4
     1680455.476      598019.903     1680562.247      597913.132
     1680796.622      597827.194      1680989.33      597772.507
#Sta/Elev= 30
       0  1063.3    45.7 1054.72    57.6 1051.12    83.4 1041.42    97.4 1040.81
   129.1  1031.1   135.1 1028.44   141.1 1024.38     165 1023.45     175 1019.97
     185 1018.88   188.9 1016.99   196.9 1016.62   206.9 1018.21   234.9 1018.29
   246.9 1016.96   252.8 1017.89   264.8 1016.01   268.8  1016.7   274.8 1019.32
   366.7 1021.16   386.6 1022.38   414.5 1025.66   458.2 1041.06   466.1 1045.49
     474 1051.81   487.9 1061.34   499.8  1066.5   527.6 1068.68     601 1077.71
#Mann= 3 , 0 , 0
       0     .08       0     185    .045       0   206.9     .08       0
Bank Sta=185,206.9
XS Rating Curve= 0 ,0
Exp/Cntr=0.3,0.1

Type RM Length L Ch R = 1 ,4382.1  ,239.5,239.6,238.8
XS GIS Cut Line= 4
     1680523.184      598150.111     1680653.393      598142.299
      1680895.58      598030.319     1680968.497      597897.507
#Sta/Elev= 30
       0  1060.9     5.9 1060.67    11.9  1059.3    41.5 1046.58    55.3 1041.93
    69.2 1038.21    75.1 1035.17    92.9  1028.5   130.4 1019.94   152.4 1018.23
   192.2 1016.92   271.8 1016.31   309.6  1016.6   317.6 1017.56   327.6 1015.06
   347.5 1015.25   356.2 1013.97   369.4 1012.94   373.4  1013.3   375.4 1014.26
   385.3 1022.26   397.3 1024.23   407.2 1029.35   419.2 1032.86   500.9 1047.58
   508.9 1048.36   514.9 1050.35   532.8 1051.24   542.8 1055.02   548.8 1056.37
#Mann= 3 , 0 , 0
       0    .065       0   356.2    .045       0   375.4      .1       0
Bank Sta=356.2,375.4
XS Rating Curve= 0 ,0
Exp/Cntr=0.3,0.1

Type RM Length L Ch R = 1 ,4142.5  ,315.5,319.3,322
XS GIS Cut Line= 4
     1680596.101      598374.069     1680731.518      598361.049
      1681051.83      598207.403     1681192.455      598121.465
#Sta/Elev= 30
       0 1038.56    15.8 1036.27    39.4 1029.35    57.2 1026.24      71 1021.25
    88.7 1018.64     152 1015.46   197.9 1014.82   267.8 1016.25   351.6 1014.77
   397.5 1013.16   421.4 1013.85   449.4 1015.59   453.4 1014.61   456.9 1012.73
   459.4 1011.64   463.4  1011.1   471.3 1011.14   475.3 1012.26   491.3 1021.26
   497.2 1025.86   499.2 1026.84   511.2 1029.19     539 1036.47   550.9 1041.37
   554.8 1042.43   600.5 1050.54   608.4 1054.12   624.3 1059.79   656.1 1069.42
#Mann= 3 , 0 , 0
       0     .06       0   456.9    .045       0   475.3      .1       0
#XS Ineff= 2 , 0
          270.33 1025.31
Permanent Ineff=
       F       F
Bank Sta=456.9,475.3
XS Rating Curve= 0 ,0
Exp/Cntr=0.3,0.1

Type RM Length L Ch R = 1 ,3823.3  ,177.2,179.3,181.4
XS GIS Cut Line= 4
     1680708.514      598647.073     1680806.171      598612.351
     1681146.882      598510.354     1681227.178      598484.312
#Sta/Elev= 30
       0 1037.15    41.9 1028.81    63.8  1023.5    71.8 1020.96    93.7 1016.15
   101.6 1014.07   117.6 1012.69   135.6 1011.93   297.5 1012.81   345.4 1012.12
   379.4 1013.34   389.4 1012.53   393.4 1010.62   397.1 1009.38   399.4 1009.01
   413.3 1008.48   415.3 1008.57   417.3 1009.18   421.3 1011.63   423.3 1013.32
   431.3 1022.71   433.3 1024.67   435.3 1026.14   443.3 1031.04   471.1 1043.08
   484.8  1046.5   488.7 1046.86   498.6 1048.79   520.2 1050.94   543.7 1055.46
#Mann= 3 , 0 , 0
       0     .06       0   397.1    .045       0   417.3      .1       0
#XS Ineff= 2 , 0
           374.9 1019.22
Permanent Ineff=
       F       F
Bank Sta=397.1,417.3
XS Rating Curve= 0 ,0
Exp/Cntr=0.3,0.1

Type RM Length L Ch R = 1 ,3643.9  ,274.6,277.6,279.1
XS GIS Cut Line= 3
     1680715.893      598767.299     1680856.518      598749.069
     1681288.809      598657.924
#Sta/Elev= 30
       0 1036.94      22 1033.52    77.9 1017.09    85.9 1015.46    97.9 1014.14
   165.8 1011.19   269.7 1012.79   345.7 1012.22   355.7 1007.15   357.7  1006.9
   375.7 1007.58   387.7 1009.35   401.7 1009.56   413.7 1010.98   435.7 1011.74
   441.7 1014.61   455.7 1027.08   459.6 1029.35   463.6 1030.25   481.6 1030.12
   495.6 1031.62   503.6 1031.33   517.6 1029.42   521.6 1028.14   525.6 1025.81
   529.6 1025.38   533.6 1026.81   539.6 1030.38   563.6 1037.62   583.6 1045.86
#Mann= 3 , 0 , 0
       0     .06       0   355.7    .045       0   375.7      .1       0
Bank Sta=355.7,375.7
XS Rating Curve= 0 ,0
Exp/Cntr=0.3,0.1

Type RM Length L Ch R = 1 ,3366.4  ,187,192.6,197.1
XS GIS Cut Line= 4
     1680757.559      598983.444     1680872.143       598980.84
     1681158.601      598936.569     1681265.372      598879.278
#Sta/Elev= 30
       0 1036.18    11.9 1033.54    17.8  1031.3    27.7 1030.71    33.6 1029.63
    41.5 1026.06    53.4 1025.31    94.8 1012.15   104.7 1010.23   118.6 1008.57
   156.6 1007.35   216.6 1008.67   276.5 1008.23   302.5 1007.02   322.5 1007.65
   343.4 1005.49   348.5 1004.78   358.4 1005.71   372.5 1006.09   382.5 1007.89
   388.5 1010.39   394.5 1013.83   408.4 1025.94   422.4 1031.44   434.3 1033.82
   444.2 1036.54     478 1042.83   503.8 1046.55   509.8 1048.13   525.6 1049.67
#Mann= 3 , 0 , 0
       0     .06       0   343.4    .045       0   358.4      .1       0
#XS Ineff= 2 , 0
          200.28 1010.61
Permanent Ineff=
       F       F
Bank Sta=343.4,358.4
XS Rating Curve= 0 ,0
Exp/Cntr=0.3,0.1

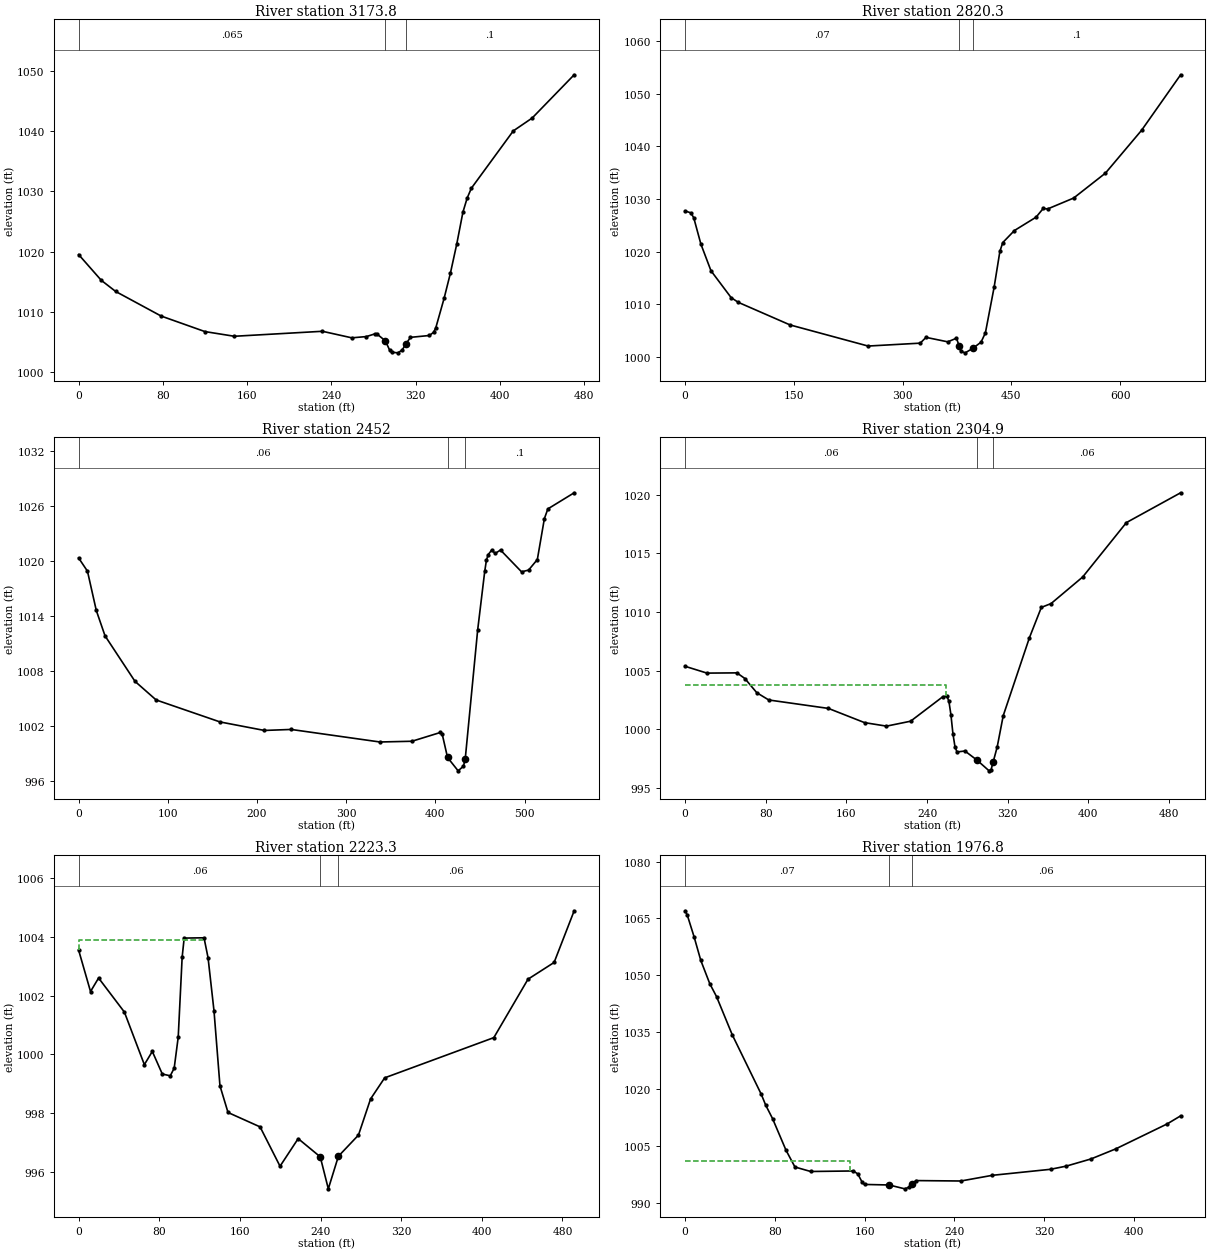
Type RM Length L Ch R = 1 ,3173.8  ,346.1,353.5,353.2
XS GIS Cut Line= 3
     1680796.622      599077.194     1680879.955      599116.257
     1681257.559      599139.694
#Sta/Elev= 30
       0 1019.49    21.5  1015.2    35.2 1013.34    78.3 1009.25   119.9 1006.66
   147.8 1005.88   231.4 1006.71   259.3 1005.62   273.2 1005.83   281.2 1006.28
   283.2 1006.26   291.2 1005.11   295.1 1003.62   297.1 1003.22   303.1 1003.12
   307.1 1003.59   310.9 1004.66     315  1005.7     333 1006.01     337 1006.55
     339 1007.26   346.9 1012.18   352.9 1016.38   358.9 1021.21   364.8 1026.56
   368.8 1028.89   372.8 1030.54   412.6 1040.09   430.5 1042.23   470.4 1049.44
#Mann= 3 , 0 , 0
       0    .065       0   291.2    .045       0   310.9      .1       0
Bank Sta=291.2,310.9
XS Rating Curve= 0 ,0
Exp/Cntr=0.3,0.1

Type RM Length L Ch R = 1 ,2820.3  ,356.6,368.3,370.6
XS GIS Cut Line= 4
     1680718.497      599335.007     1680882.559      599405.319
     1681142.976      599431.361     1681335.684      599282.924
#Sta/Elev= 30
       0 1027.73     7.9 1027.36    11.9 1026.44    21.8 1021.42    35.7 1016.36
    63.5 1011.26    73.4 1010.36   144.8 1006.07   252.4 1002.06   324.3 1002.61
   332.3 1003.71   362.3 1002.86   374.3 1003.55   378.3 1001.98   380.3 1001.04
   386.3 1000.77   396.7 1001.61   408.2  1002.8   414.2 1004.56   426.2 1013.21
   434.2 1020.06   438.2 1021.72   454.2    1024   484.1 1026.54     494  1028.2
     500  1028.1   535.9 1030.17   579.8 1034.91   629.6 1043.04   683.5 1053.59
#Mann= 3 , 0 , 0
       0     .07       0   378.3    .045       0   396.7      .1       0
Bank Sta=378.3,396.7
XS Rating Curve= 0 ,0
Exp/Cntr=0.3,0.1

Type RM Length L Ch R = 1 ,2452    ,150,147.1,143.5
XS GIS Cut Line= 4
     1680717.195      599467.385      1680790.98      599549.851
     1681057.039      599746.465     1681137.768      599827.194
#Sta/Elev= 30
       0 1020.32     9.9 1018.88    19.8 1014.59    29.6 1011.82    63.2 1006.85
    86.9 1004.82   158.5 1002.42   208.3 1001.49   238.2  1001.6   337.8 1000.23
   373.7 1000.31   405.6 1001.27   407.6 1001.11   413.6  998.54   425.5  997.08
   431.5  997.59   433.5  998.42   447.4 1012.46   455.3 1018.85   457.2 1020.07
   459.2 1020.69   463.1 1021.18   467.1 1020.82     473 1021.19   496.6 1018.81
   504.5    1019   514.3 1020.15   522.2 1024.62   526.1 1025.68   555.6 1027.44
#Mann= 3 , 0 , 0
       0     .06       0   413.6    .045       0   433.5      .1       0
Bank Sta=413.6,433.5
XS Rating Curve= 0 ,0
Exp/Cntr=0.3,0.1

Type RM Length L Ch R = 1 ,2304.9  ,82.7,81.5,79.1
XS GIS Cut Line= 6
     1680653.393      599723.028     1680788.809      599759.486
     1680856.518      599788.132     1680971.101      599853.236
     1681030.997      599881.882     1681109.122      599897.507
#Sta/Elev= 30
       0 1005.38    21.7  1004.8    51.4 1004.82    59.3 1004.34    71.1 1003.13
      83 1002.51   142.2 1001.79     178 1000.58   199.8 1000.28   223.7  1000.7
   255.7 1002.79   259.7 1002.83   261.7 1002.41   263.7 1001.26   265.7  999.64
   267.7  998.54   269.7  998.08   277.6  998.16   289.5  997.39   301.6  996.47
   303.6  996.58   305.6  997.22   309.6   998.5   315.6 1001.17   341.6 1007.82
   353.4  1010.4   363.1 1010.73   394.4 1012.99   437.8 1017.63   491.6 1020.17
#Mann= 3 , 0 , 0
       0     .06       0   289.5    .045       0   305.6     .06       0
#XS Ineff= 2 , 0
          259.31 1003.76
Permanent Ineff=
       F       F
Bank Sta=289.5,305.6
XS Rating Curve= 0 ,0
Exp/Cntr=0.3,0.1

Type RM Length L Ch R = 1 ,2223.3  ,266.4,246.6,227
XS GIS Cut Line= 6
     1680619.539      599782.924     1680754.955      599819.382
     1680822.664      599848.028     1680937.247      599913.132
     1680997.143      599941.778     1681075.268      599957.403
#Sta/Elev= 30
       0 1003.55    11.8 1002.14    19.8  1002.6    45.4 1001.44    65.2  999.65
    73.1  1000.1      83  999.33    90.9  999.27    94.8  999.53    98.8 1000.59
   102.7 1003.31   104.7 1003.96   124.4 1003.97   128.4 1003.29   134.3 1001.48
   140.2  998.93   148.2  998.02     180  997.53   199.8  996.19   217.8  997.13
   239.7  996.51   247.7  995.42   257.7  996.53   277.6  997.25   289.6  998.48
   303.6   999.2   411.9 1000.57   445.8 1002.56   471.7 1003.13   491.6 1004.89
#Mann= 3 , 0 , 0
       0     .06       0   239.7    .045       0   257.7     .06       0
#XS Ineff= 2 , 0
          123.45 1003.89
Permanent Ineff=
       F       F
Bank Sta=239.7,257.7
XS Rating Curve= 0 ,0
Exp/Cntr=0.3,0.1

Type RM Length L Ch R = 1 ,1976.8  ,390.1,390.7,385.5
XS GIS Cut Line= 2
     1680736.726       600137.09     1681137.768      599952.194
#Sta/Elev= 30
       0 1067.03       2 1065.84       8 1060.17      14 1053.91      22 1047.78
      28 1044.38      42  1034.3    67.9 1018.57    71.9 1015.67    77.9 1012.19
    89.9 1003.83    97.9  999.38   111.9   998.2   149.9  998.34   153.9  997.56
   157.9   995.3   159.9  994.78   181.8  994.64   195.8  993.62   199.8  994.09
   201.8  994.91   205.8   995.8   245.8  995.69   273.8  997.19   325.7  998.78
   339.7  999.62   361.7 1001.51   383.7 1004.16   429.6 1010.76   441.6 1012.89
#Mann= 3 , 0 , 0
       0     .07       0   181.8    .045       0   201.8     .06       0
#XS Ineff= 2 , 0
           146.9 1000.94
Permanent Ineff=
       F       F
Bank Sta=181.8,201.8
XS Rating Curve= 0 ,0
Exp/Cntr=0.3,0.1

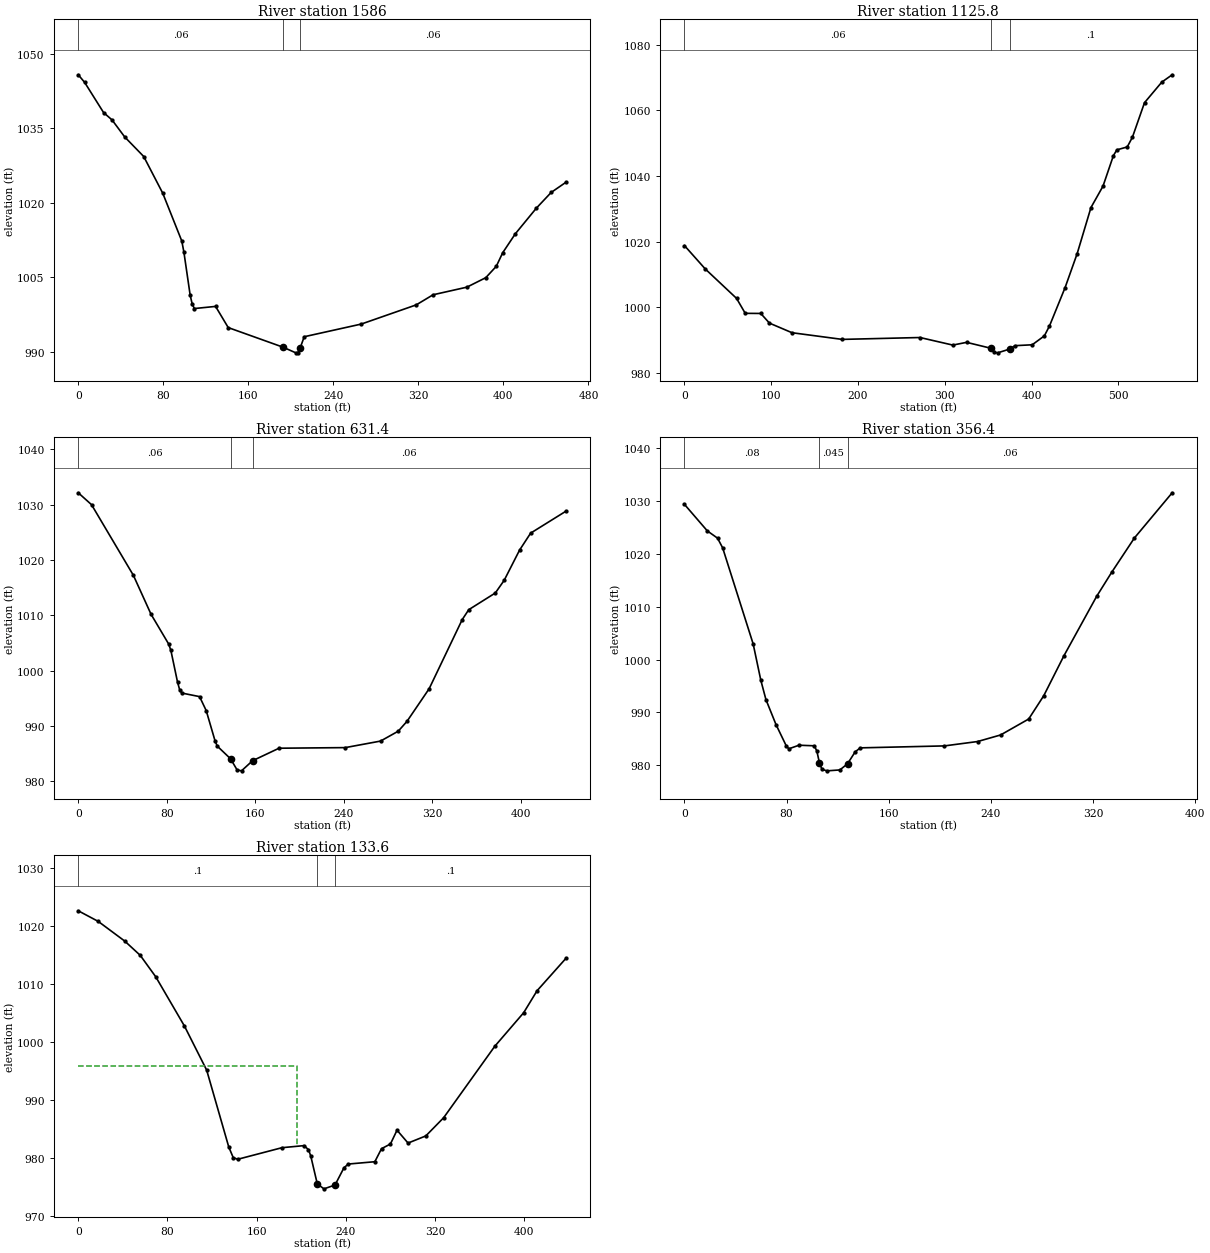
Type RM Length L Ch R = 1 ,1586    ,456.2,460.2,459.3
XS GIS Cut Line= 3
     1680981.518      600419.642     1681234.122      600250.371
     1681340.893      600138.392
#Sta/Elev= 30
       0 1045.72       6  1044.2    23.8 1038.13    31.8 1036.64    43.7 1033.22
    61.6 1029.28    79.5  1021.9    97.4 1012.29    99.4 1010.05   105.3 1001.38
   107.3  999.53   109.3   998.7   129.2  999.13   141.1  994.87   192.5  990.94
   204.7  989.79   206.7  989.85   208.7  990.73   212.6  993.03   266.3  995.58
     318  999.44   333.8 1001.47   365.6    1003   383.4 1004.91   393.3  1007.2
   399.3 1009.92   411.2 1013.74     431  1018.9   444.9 1022.05   458.8  1024.1
#Mann= 3 , 0 , 0
       0     .06       0   192.5    .045       0   208.7     .06       0
Bank Sta=192.5,208.7
XS Rating Curve= 0 ,0
Exp/Cntr=0.3,0.1

Type RM Length L Ch R = 1 ,1125.8  ,493.6,494.5,491.7
XS GIS Cut Line= 3
     1681122.143      600694.382     1681278.393      600660.528
     1681601.309      600420.944
#Sta/Elev= 30
       0 1018.82      24  1011.7      60 1002.77      70  998.22    87.9  998.18
    97.9  995.24   123.9  992.32   181.8  990.29   271.4  990.86   309.2  988.56
   325.1  989.39     353   987.6   356.9  986.36   360.9   986.2     375  987.37
   380.8  988.38   400.7  988.65   414.7  991.36   420.6  994.37   438.6 1006.05
   452.5 1016.38   468.4  1030.4   482.3 1036.92   494.3 1046.22   498.3 1047.96
   510.2 1048.83   516.2 1051.81   530.1  1062.3     550 1068.55     562 1070.79
#Mann= 3 , 0 , 0
       0     .06       0     353    .045       0     375      .1       0
Bank Sta=353,375
XS Rating Curve= 0 ,0
Exp/Cntr=0.3,0.1

Type RM Length L Ch R = 1 ,631.4   ,273.8,274.9,275
XS GIS Cut Line= 2
     1681278.393       601043.34     1681603.914      600746.465
#Sta/Elev= 30
       0 1032.15      12    1030    49.8 1017.23    65.8 1010.17    81.7  1004.8
    83.7 1003.64    89.7  997.92    91.7  996.48    93.7  995.93   109.6  995.29
   115.6  992.77   123.6  987.29   125.6  986.34   137.6  984.05   143.5  982.04
   147.5  981.87   157.5   983.7   181.4  985.96   241.2  986.07   273.1  987.25
   289.1  989.04     297  990.82     317  996.71   346.9 1009.22   352.8 1011.01
   376.8 1014.03   384.8 1016.32   398.7 1021.78   408.7 1024.85   440.6 1028.82
#Mann= 3 , 0 , 0
       0     .06       0   137.6    .045       0   157.5     .06       0
Bank Sta=137.6,157.5
XS Rating Curve= 0 ,0
Exp/Cntr=0.3,0.1

Type RM Length L Ch R = 1 ,356.4   ,219.9,222.9,225.8
XS GIS Cut Line= 4
     1681499.747      601196.986     1681559.643      601147.507
     1681700.268      601019.903     1681775.789      600933.965
#Sta/Elev= 30
       0 1029.38    17.9 1024.36    25.9 1022.99    29.9 1021.15    53.8 1002.96
    59.8  996.08    63.8  992.43    71.7  987.69    79.7  983.68    81.7  983.11
    89.7  983.79   101.7  983.68   103.7  982.67   105.7  980.45   107.7  979.21
   111.7  978.94   121.7  979.11   127.7  980.27   133.7  982.54   137.7  983.29
   203.6  983.66   229.6  984.49   247.6  985.73   269.6  988.75   281.4  993.16
   297.2 1000.72   322.8 1011.96   334.6 1016.52   352.4 1023.02     382 1031.58
#Mann= 3 , 0 , 0
       0     .08       0   105.7    .045       0   127.7     .06       0
Bank Sta=105.7,127.7
XS Rating Curve= 0 ,0
Exp/Cntr=0.3,0.1

Type RM Length L Ch R = 1 ,133.6   ,126.9,133.6,138.7
XS GIS Cut Line= 4
     1681559.643      601298.549     1681692.455      601306.361
     1681836.987      601201.326     1681908.601      601098.028
#Sta/Elev= 30
       0 1022.65    17.9 1020.82    41.7 1017.42    55.6 1014.96    69.5 1011.26
    95.3 1002.74   115.2  995.14     135  981.88     139  980.05     143  979.76
   182.7  981.76   202.5  982.12   206.5  981.42   208.5  980.36   214.4  975.51
   220.4  974.66   230.3  975.32   238.3  978.29   242.2  978.94     266  979.34
     272  981.59     280   982.4   285.9  984.78   295.8  982.56   311.7  983.79
   327.7  986.93   373.6  999.27   399.5 1005.06   411.5 1008.85   437.4 1014.44
#Mann= 3 , 0 , 0
       0      .1       0   214.4    .045       0   230.3      .1       0
#XS Ineff= 2 , 0
          196.63  995.87
Permanent Ineff=
       F       F
Bank Sta=214.4,230.3
XS Rating Curve= 0 ,0
Exp/Cntr=0.3,0.1

Chan Stop Cuts=-1
Use User Specified Reach Order=0
Composite Channel Slope=5